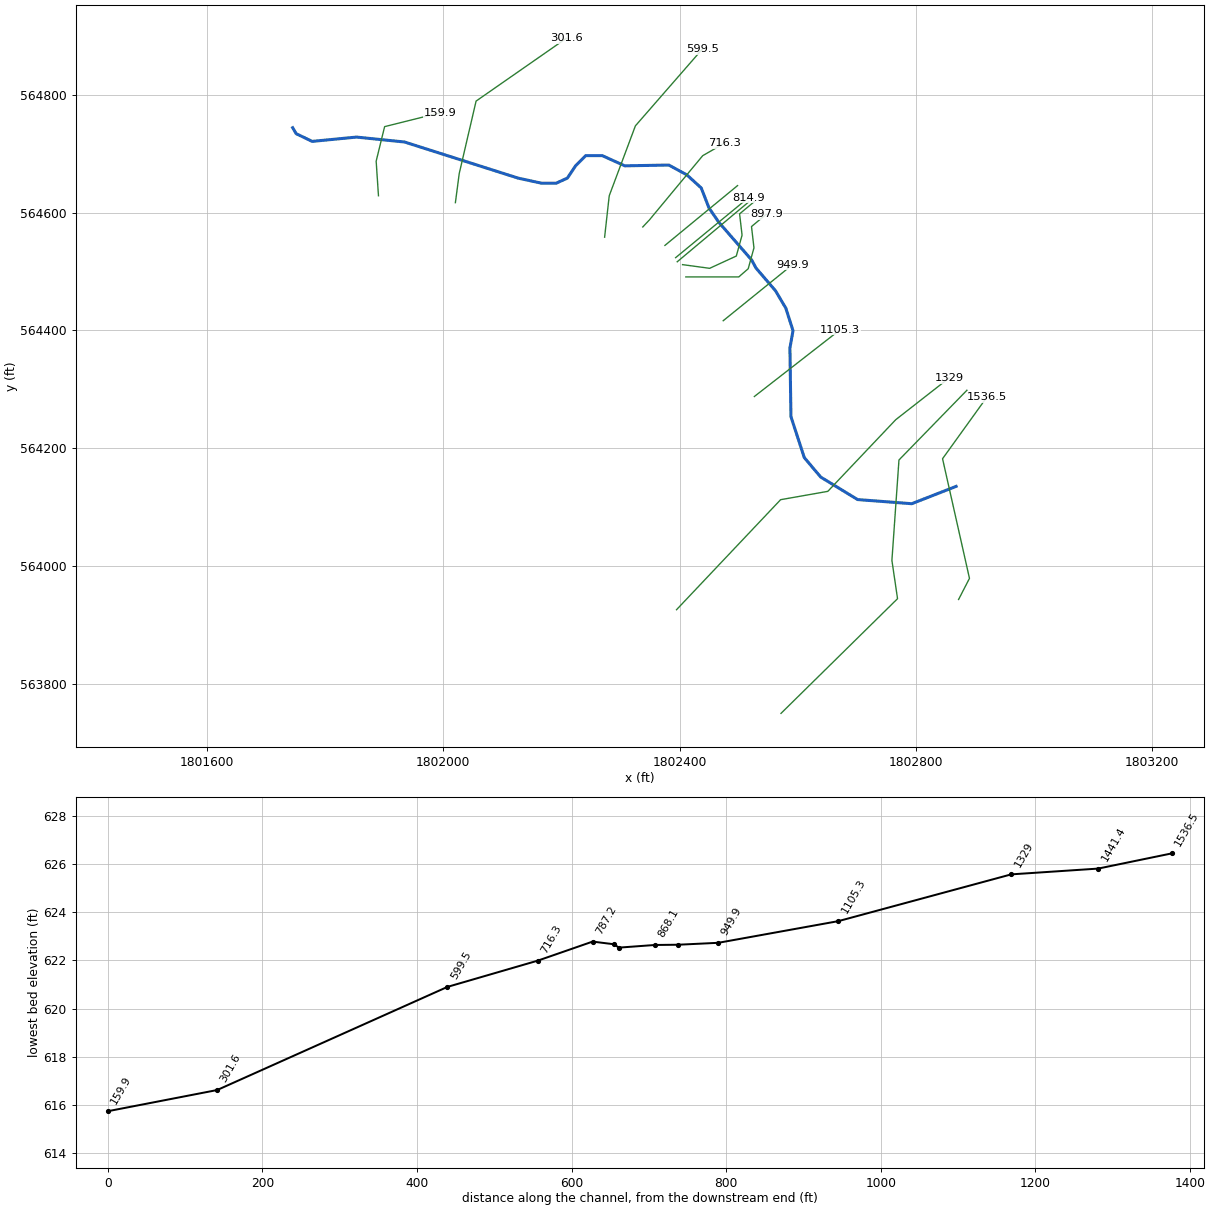
--- RACCOONCR.prj (project) ---

Proj Title=RACCOONCR
Current Plan=p01
Default Exp/Contr=0,0
English Units
Geom File=g01
Flow File=f01
Plan File=p01
BEGIN DESCRIPTION:
END DESCRIPTION:
DSS File=dss
DSS Export Rating Curves= 0
DSS Export Rating Curve Sorted= 0
DSS Export Volume Flow Curves= 0
DXF OffsetX= 0
DXF OffsetY= 0
DXF ScaleX= 0
DXF ScaleY= 0

--- RACCOONCR.p01 (plan) ---

Plan Title=Floodplain
Program Version=4.10
Short Identifier=Floodplain
Geom File=g01
Flow File=f01
Subcritical Flow
K Sum by GR= 0
Std Step Tol= 0.01
Critical Tol= 0.01
Num of Std Step Trials= 20
Max Error Tol= 0.3
Flow Tol Ratio= 0.001
Split Flow NTrial= 30
Split Flow Tol= 0.02
Split Flow Ratio= 0.02
Log Output Level= 0
Friction Slope Method= 1
Unsteady Friction Slope Method= 2
Unsteady Bridges Friction Slope Method= 1
Parabolic Critical Depth
Global Vel Dist= 0 , 0 , 0
Global Log Level= 0
CheckData=True
Encroach Param=-1 ,0,0, 0
Run HTab= 0
Run UNet= 0
Run PostProcess= 0
Run WQNet= 0
UNET Theta= 0
UNET Theta Warmup= 0
UNET ZTol= 0
UNET ZSATol= 0
UNET MxIter= 0
UNET MaxInSteps= 0
UNET DtIC= 0
UNET DtMin= 0
UNET MaxCRTS= 0
UNET WFStab= 0
UNET SFStab= 0
UNET WFX= 1
UNET SFX= 1
UNET DSS MLevel= 1
UNET DZMax Abort= 0
UNET Convert EG Bridges= 0
UNET Use Existing IB Tables= 0
UNET Froude Reduction=False
UNET Froude Limit= 0
UNET Froude Power= 0
UNET Time Slicing=0,0, 5
UNET Junction Losses=0
DSS File=dss
Write IC File= 0
Write IC File at Sim End=0
Echo Input=False
Echo Parameters=False
Echo Output=False
Write Detailed= 0
WQ AD Non Conservative
WQ ULTIMATE=-1
WQ Max Comp Step=1HOUR
WQ Output Interval=15MIN
WQ Output Selected Increments= 0
WQ Output face flow=0
WQ Output face velocity=0
WQ Output face area=0
WQ Output face dispersion=0
WQ Output cell volume=0
WQ Output cell surface area=0
WQ Output cell continuity=0
WQ Output cumulative cell continuity=0
WQ Output face conc=0
WQ Output face dconc_dx=0
WQ Output face courant=0
WQ Output face peclet=0
WQ Output face adv mass=0
WQ Output face disp mass=0
WQ Output cell mass=0
WQ Output cell source sink temp=0
WQ Output cell source sink nsm=0
WQ Output MaxMinRange=-1
WQ Daily Max Min Mean=-1
WQ Daily Range=0
WQ Daily Time=0
WQ Create Restart=0
WQ Fixed Restart=0
WQ System Summary=0
WQ Use Fixed Temperature=0
Sorting and Armoring Iterations= 10
XS Update Threshold= 0.02
Hydraulics Update Threshold= 0.02
Energy Slope Method= 1
Volume Change Method= 0
XS Weighting Method= 0
Number of US Weighted Cross Sections= 1
Number of DS Weighted Cross Sections= 1
Upstream XS Weight=0.25
Main XS Weight=0.5
Downstream XS Weight=0.25
Number of DS XS's Weighted with US Boundary= 1
Upstream Boundary Weight= 1
Weight of XSs Associated with US Boundary= 0
Number of US XS's Weighted with DS Boundary= 1
Downstream Boundary Weight= 0.5
Weight of XSs Associated with DS Boundary= 0.5
Sediment Output Level= 4
Mass or Volume Output= 0
Output Increment Type= 1
Profile and TS Output Increment= 10
XS Output Flag= 0
XS Output Increment= 10
Disregard all LS=0
Disregard all Conn=0
Disregard all Breaches=0
Disregard all Pumps=0

--- RACCOONCR.f01 (steady flow) ---

Flow Title=NFF Regression Equation
Program Version=4.10
Number of Profiles= 1
Profile Names=P100yr
River Rch & RM=RACCOONCR,Main            ,1536.5
892.8928
River Rch & RM=RACCOONCR,Main            ,1105.3
953.7839
Boundary for River Rch & Prof#=RACCOONCR,Main            , 1
Up Type= 0
Dn Type= 3
Dn Slope=0.006
DSS Import GetInterval= 0
DSS Import GetPeak= 0
DSS Import FillOption= 0

--- RACCOONCR.g01 (geometry) ---

Geom Title=USGS 10m DEM
Program Version=4.10

River Reach=RACCOONCR       ,Main
Reach XY= 30
     1802868.108      564135.654     1802793.113      564106.273
     1802701.411      564113.265      1802638.91      564151.459
     1802611.133      564184.446     1802588.563       564253.89
     1802586.827       564370.21     1802592.035      564399.723
     1802579.883      564437.918     1802562.413      564467.371
     1802529.358      564505.936     1802522.136      564519.454
      1802466.58      564583.343     1802449.913      564607.649
     1802436.719      564641.676     1802412.413      564663.899
     1802381.858      564680.565     1802307.313      564679.237
     1802269.119      564696.598     1802241.341      564696.598
      1802223.98      564679.237     1802210.091      564658.404
     1802190.994      564649.723     1802166.688      564649.723
     1802126.758      564658.404     1801934.431      564719.654
     1801853.181      564727.987     1801778.181      564720.695
     1801751.098      564733.716     1801745.107      564743.946

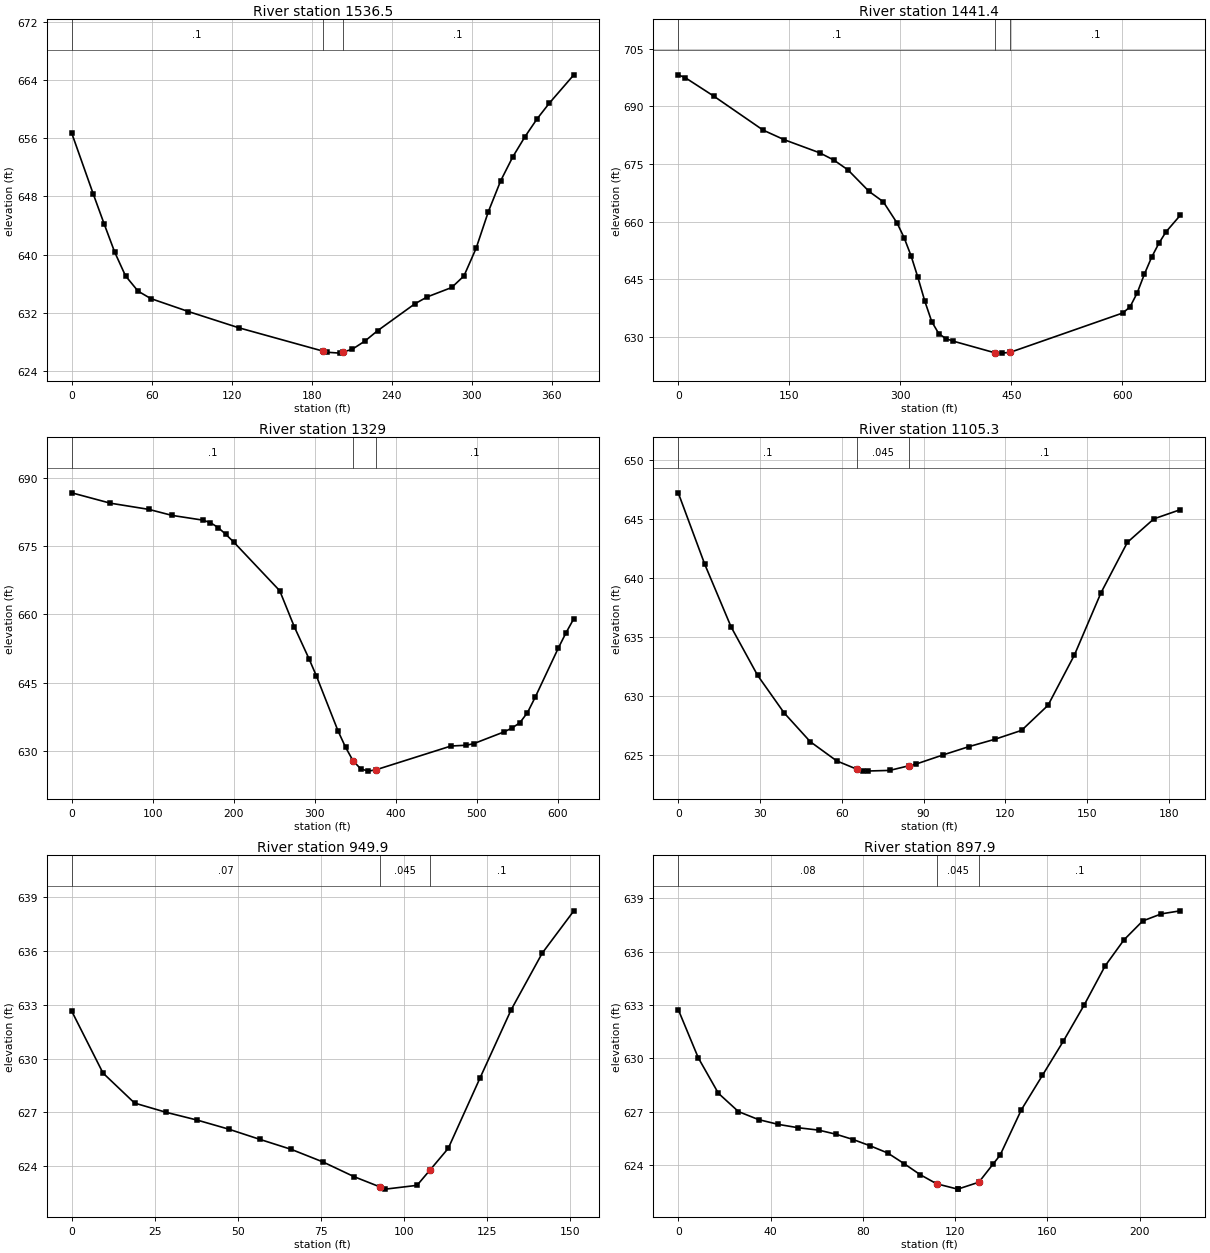
Type RM Length L Ch R = 1 ,1536.5  ,101.8,95.2,88.5
XS GIS Cut Line= 4
     1802872.309      563943.847     1802890.755      563979.654
     1802845.182      564182.562     1802920.052      564286.729
#Sta/Elev= 28
       0  656.69    16.1  648.34    24.2  644.26    32.2  640.33    40.3  637.07
    49.7  634.97    59.2  633.95    87.5  632.16   125.4  629.92   188.1  626.73
   191.5  626.56     201  626.44   203.1  626.56   210.4  626.98   219.9  628.11
   229.3  629.52   257.4  633.24   266.6  634.18   284.9  635.47   294.1  637.06
   303.2  640.86   312.4  645.91   321.6  650.14   330.7  653.44   339.9  656.23
     349  658.69   358.2  660.85   376.5  664.73
#Mann= 3 , 0 , 0
       0      .1       0   188.1    .045       0   203.1      .1       0
Bank Sta=188.1,203.1
XS Rating Curve= 0 ,0
Exp/Cntr=0.3,0.1

Type RM Length L Ch R = 1 ,1441.4  ,135.6,112.4,96.6
XS GIS Cut Line= 5
     1802571.745      563750.704     1802768.994      563945.217
     1802759.462      564010.036     1802771.398      564180.392
     1802886.415      564298.664
#Sta/Elev= 30
       0  698.17     9.6  697.41    47.8  692.66   114.6   683.8   143.3  681.29
     191   677.9   210.2  676.01   229.3  673.45   257.9  667.84     277  665.17
   295.7  659.62   305.1  655.85   314.5  651.14   323.8  645.48   333.2  639.27
   342.5  633.99     352  630.87   361.5   629.6     371  628.95   427.9  625.89
   437.4  625.81   448.6  626.03   600.6  636.25   610.4  637.84   620.1  641.49
   629.8  646.36   639.5  650.72   649.2  654.32   658.9  657.33   678.3  661.66
#Mann= 3 , 0 , 0
       0      .1       0   427.9    .045       0   448.6      .1       0
Bank Sta=427.9,448.6
XS Rating Curve= 0 ,0
Exp/Cntr=0.3,0.1

Type RM Length L Ch R = 1 ,1329    ,217.3,223.6,222.6
XS GIS Cut Line= 5
     1802394.879      563926.486     1802571.054      564113.064
     1802650.955      564127.223     1802765.972      564248.751
     1802856.033      564319.281
#Sta/Elev= 30
       0  686.65    47.5  684.38      95  683.02   123.6   681.7   161.6  680.66
   171.1   680.1   180.6  679.03   190.1  677.53   199.6  675.89   256.6  665.16
   274.6  657.24   292.7  650.24   301.7  646.52   328.7  634.32   337.8  630.82
     347  627.86   356.4  626.09   365.6  625.57   374.9  625.84   467.9  631.08
   486.5  631.25   495.8  631.59   533.7   634.2   543.2  635.04   552.8  636.17
   562.3  638.42   571.8  641.78   600.4   652.6   609.9  655.95   619.5  659.04
#Mann= 3 , 0 , 0
       0      .1       0     347    .045       0   374.9      .1       0
Bank Sta=347,374.9
XS Rating Curve= 0 ,0
Exp/Cntr=0.3,0.1

Type RM Length L Ch R = 1 ,1105.3  ,157,155.4,153.5
XS GIS Cut Line= 2
     1802526.649      564288.074     1802671.788      564401.268
#Sta/Elev= 23
       0  647.25     9.7   641.2    19.4  635.86    29.1  631.76    38.8  628.58
    48.4  626.13    58.1   624.5   65.54  623.79    67.8  623.63    69.5  623.64
    77.5  623.69    84.5  624.08    87.2  624.23    96.9  624.99   106.6  625.71
   116.2  626.34   125.9  627.09   135.6  629.22   145.3   633.5     155  638.76
   164.7  643.05   174.4  645.04   184.1  645.82
#Mann= 3 , 0 , 0
       0      .1       0   65.54    .045       0    84.5      .1       0
Bank Sta=65.54,84.5
XS Rating Curve= 0 ,0
Exp/Cntr=0.3,0.1

Type RM Length L Ch R = 1 ,949.9   ,41.6,52,72.5
XS GIS Cut Line= 2
     1802473.872      564416.546     1802591.233      564511.685
#Sta/Elev= 19
       0  632.63     9.4  629.19    18.9  627.52    28.3  627.01    37.8  626.57
    47.2  626.07    56.6   625.5    66.1  624.94    75.5  624.25      85  623.42
    92.8  622.85    94.4  622.73   103.9  622.94   107.8  623.79   113.3     625
   122.8  628.89   132.2   632.7   141.6  635.87   151.1  638.22
#Mann= 3 , 0 , 0
       0     .07       0    92.8    .045       0   107.8      .1       0
Bank Sta=92.8,107.8
XS Rating Curve= 0 ,0
Exp/Cntr=0.3,0.1

Type RM Length L Ch R = 1 ,897.9   ,29.7,29.8,31
XS GIS Cut Line= 6
     1802410.677      564490.852     1802500.261      564490.852
     1802516.233      564504.741     1802525.955      564540.157
     1802521.788      564576.268     1802546.788      564597.102
#Sta/Elev= 29
       0  632.75     8.7  630.03    17.4  628.04    26.1  627.01    34.8  626.56
    43.4  626.29    52.1   626.1    60.8  625.97    68.3  625.74    75.8  625.44
    83.3  625.08    90.8  624.68    97.8  624.09   104.9  623.46     112  622.95
   121.1  622.65   121.4  622.66   130.3  623.04   136.4  624.05   139.5  624.56
   148.7  627.11   157.8  629.04   166.9  630.97     176  633.02     185   635.2
   193.2  636.67   201.3  637.73   209.4  638.13   217.6   638.3
#Mann= 3 , 0 , 0
       0     .08       0     112    .045       0   130.3      .1       0
Bank Sta=112,130.3
XS Rating Curve= 0 ,0
Exp/Cntr=0.3,0.1

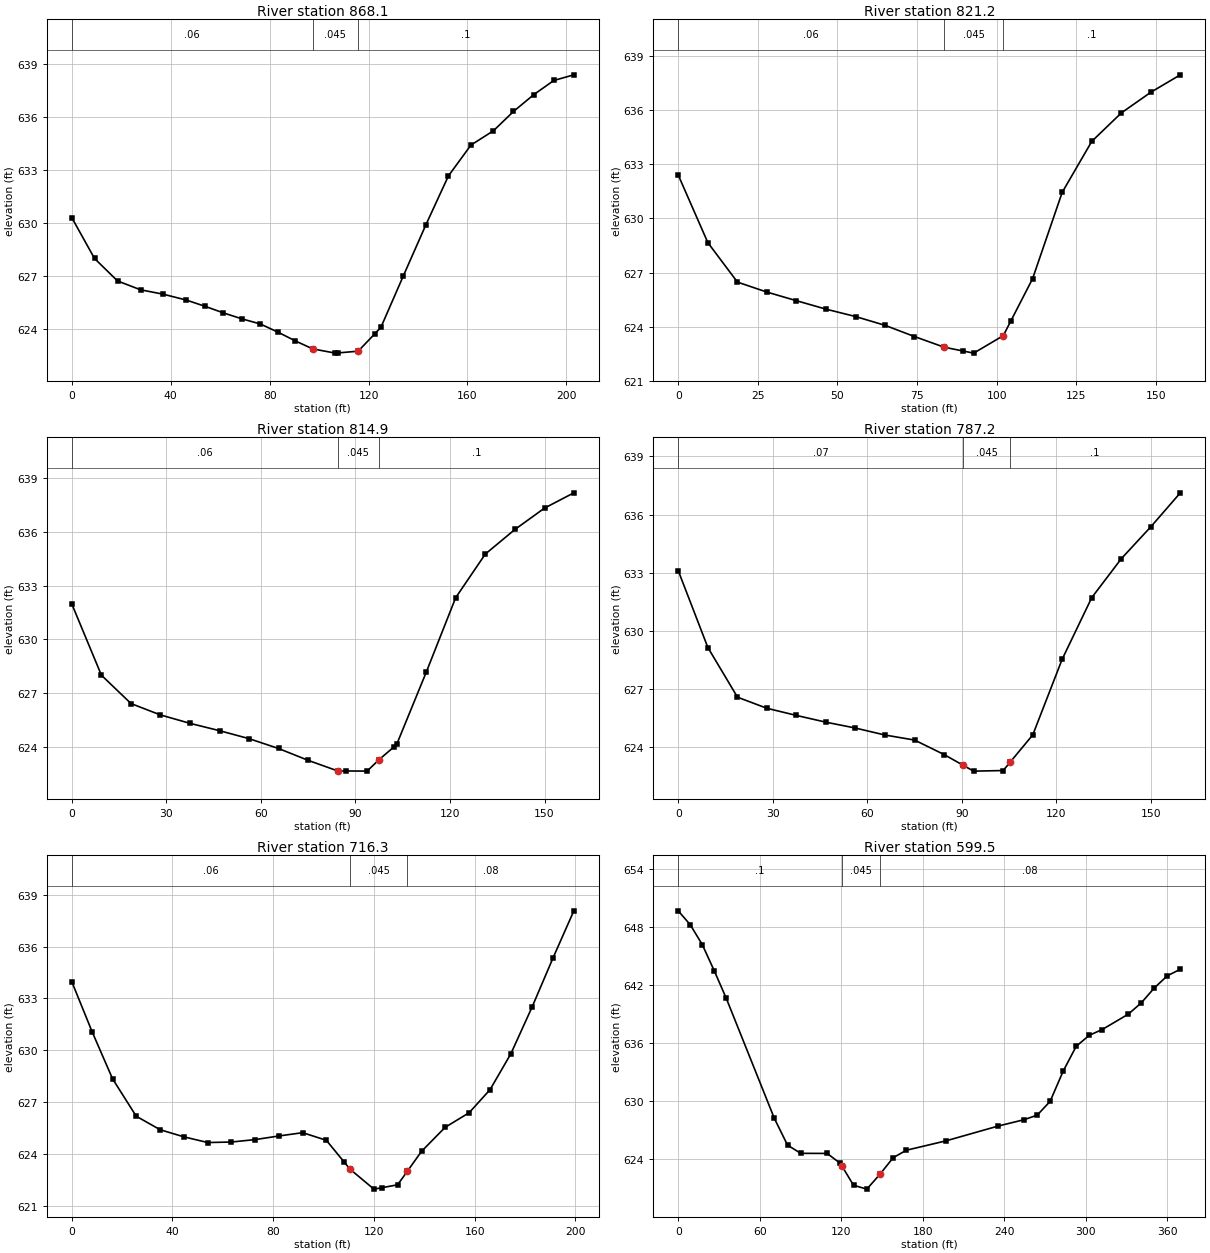
Type RM Length L Ch R = 1 ,868.1   ,57,46.8,25.5
XS GIS Cut Line= 6
     1802405.122      564511.685     1802450.955      564505.435
     1802496.094      564526.268     1802505.816      564561.685
     1802501.649      564597.796     1802526.649       564618.63
#Sta/Elev= 27
       0   630.3     9.2  627.99    18.5  626.72    27.8  626.22      37  625.97
    46.3  625.64    53.8  625.29    61.2  624.92    68.7  624.58    76.2  624.29
    83.3  623.83    90.4  623.33    97.4  622.88   106.6  622.64   107.5  622.65
   115.8  622.75   122.5  623.73     125   624.1   134.1  627.02   143.2   629.9
   152.3  632.66   161.4   634.4   170.5  635.21   178.6   636.3   186.8  637.25
   194.9  638.05     203  638.37
#Mann= 3 , 0 , 0
       0     .06       0    97.4    .045       0   115.8      .1       0
Bank Sta=97.4,115.8
XS Rating Curve= 0 ,0
Exp/Cntr=0.3,0.1

Type RM Length L Ch R = 1 ,821.2   ,6.5,6.3,6.1
XS GIS Cut Line= 2
     1802396.094      564516.546     1802516.927      564617.935
#Sta/Elev= 20
       0  632.41     9.3  628.66    18.6  626.47    27.8  625.92    37.1  625.44
    46.4  624.97    55.7  624.56      65  624.07    74.2  623.45    83.5  622.86
    89.4  622.65    92.8  622.53   102.1   623.5   104.4  624.29   111.3  626.66
   120.6  631.45   129.9  634.28   139.2  635.86   148.5  637.01   157.7  637.97
#Mann= 3 , 0 , 0
       0     .06       0    83.5    .045       0   102.1      .1       0
Bank Sta=83.5,102.1
XS Rating Curve= 0 ,0
Exp/Cntr=0.3,0.1

Type RM Length L Ch R = 1 ,814.9   ,27.7,27.7,27.8
XS GIS Cut Line= 2
     1802393.316      564523.491     1802516.233       564624.88
#Sta/Elev= 21
       0  631.98     9.4  628.01    18.8  626.43    28.1   625.8    37.5  625.33
    46.9  624.92    56.2  624.48    65.6  623.93      75  623.27    84.4  622.68
    87.1  622.68    93.7  622.67    97.5  623.31   102.1     624   103.1  624.16
   112.5  628.19   121.8  632.32   131.2  634.75   140.6  636.12     150  637.31
   159.3  638.16
#Mann= 3 , 0 , 0
       0     .06       0    84.4    .045       0    97.5      .1       0
Bank Sta=84.4,97.5
XS Rating Curve= 0 ,0
Exp/Cntr=0.3,0.1

Type RM Length L Ch R = 1 ,787.2   ,66.5,70.9,75.2
XS GIS Cut Line= 2
     1802375.261      564544.324     1802498.177      564645.713
#Sta/Elev= 20
       0  633.11     9.4  629.15    18.8  626.59    28.1  626.02    37.5  625.65
    46.9   625.3    56.2     625    65.6  624.64      75  624.38    84.4  623.63
    90.3  623.09    93.7  622.78   103.1  622.81   105.3  623.24   112.5  624.65
   121.8  628.54   131.2  631.72   140.6  633.73     150  635.38   159.3  637.12
#Mann= 3 , 0 , 0
       0     .07       0    90.3    .045       0   105.3      .1       0
Bank Sta=90.3,105.3
XS Rating Curve= 0 ,0
Exp/Cntr=0.3,0.1

Type RM Length L Ch R = 1 ,716.3   ,109.1,116.9,124.3
XS GIS Cut Line= 4
     1802337.761      564575.574     1802348.872       564587.38
     1802439.149      564696.407     1802475.261      564717.241
#Sta/Elev= 26
       0  633.97     8.1  631.07    16.2  628.36    25.6   626.2    35.1  625.42
    44.5  625.01      54  624.68    63.4  624.71    72.8  624.85    82.3  625.06
    91.7  625.25   101.1  624.81   108.1  623.57   110.6  623.13     120  621.99
   123.1  622.07   129.4  622.24  133.22  623.01   138.9  624.17   148.3  625.56
   157.8   626.4   166.1  627.73   174.4  629.81   182.8   632.5   191.1  635.33
   199.4  638.06
#Mann= 3 , 0 , 0
       0     .06       0   110.6    .045       0  133.22     .08       0
Bank Sta=110.6,133.22
XS Rating Curve= 0 ,0
Exp/Cntr=0.3,0.1

Type RM Length L Ch R = 1 ,599.5   ,294.2,297.9,301.3
XS GIS Cut Line= 4
     1802273.177      564558.213      1802280.99      564628.525
     1802325.261      564747.015     1802438.542      564877.223
#Sta/Elev= 30
       0  649.67     8.8  648.24    17.7  646.18    26.5  643.48    35.4  640.62
    70.8  628.21    80.5  625.45    90.2   624.6   109.7  624.59   119.4  623.56
   120.4  623.33   129.1   621.3   138.9   620.9   148.6  622.44   158.3  624.15
     168  624.92   197.2  625.89   235.6  627.42   254.8  628.08   264.4  628.55
   273.9  629.97   283.5  633.09   293.1  635.66   302.7   636.8   312.3   637.4
   331.5  638.99   341.1  640.16   350.6  641.69   360.2  642.95   369.8  643.63
#Mann= 3 , 0 , 0
       0      .1       0   120.4    .045       0   148.6     .08       0
Bank Sta=120.4,148.6
XS Rating Curve= 0 ,0
Exp/Cntr=0.3,0.1

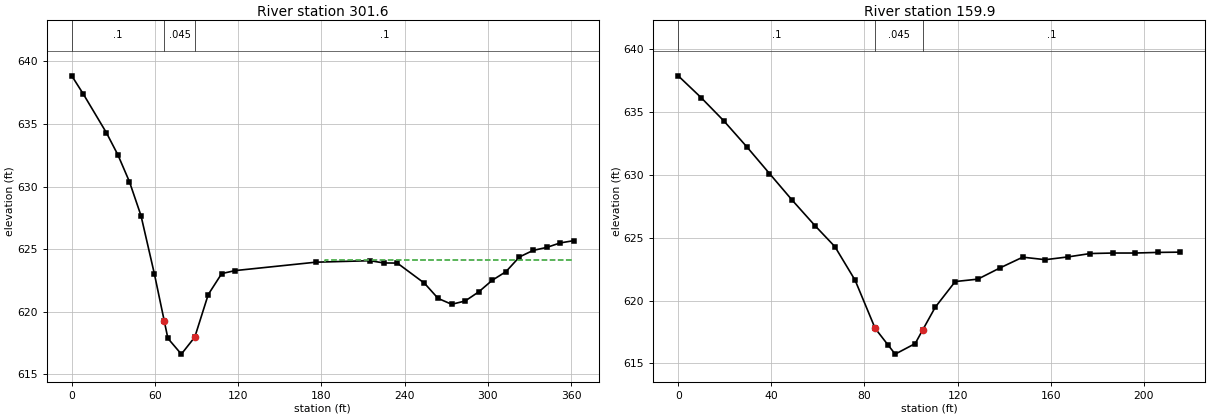
Type RM Length L Ch R = 1 ,301.6   ,142.2,141.6,141.6
XS GIS Cut Line= 4
     1802020.573      564616.807     1802027.083      564666.286
     1802055.601      564789.035     1802208.247      564895.453
#Sta/Elev= 30
       0  638.84     8.3  637.39      25  634.29    33.3  632.52    41.6  630.38
    49.9  627.68    59.6  623.01    66.7  619.26    69.3  617.88      79  616.62
    88.7  617.98    98.4  621.38   108.1  623.05   117.8  623.29   175.9  623.96
   215.1  624.08   224.9   623.9   234.7  623.89   254.3  622.28   264.1  621.07
   273.9   620.6   283.6  620.86   293.4  621.59   303.2  622.52     313   623.2
   322.8  624.38   332.6   624.9   342.4  625.14   352.2   625.5     362  625.68
#Mann= 3 , 0 , 0
       0      .1       0    66.7    .045       0    88.7      .1       0
#XS Ineff= 2 , 0
                          182.46          624.15
Permanent Ineff=
       F       F
Bank Sta=66.7,88.7
XS Rating Curve= 0 ,0
Exp/Cntr=0.3,0.1

Type RM Length L Ch R = 1 ,159.9   ,178.4,159.9,141
XS GIS Cut Line= 4
     1801890.365      564628.525     1801886.458      564687.119
     1801900.781      564745.713     1801994.531       564769.15
#Sta/Elev= 26
       0   637.9     9.8  636.17    19.6  634.31    29.4  632.26    39.2  630.12
    48.9  628.01    58.7  625.98    67.3   624.3      76  621.62    84.6  617.79
      90   616.5    93.2  615.74   101.8  616.58     105  617.66   110.4  619.47
     119  621.52   128.7  621.71   138.4  622.62     148  623.46   157.7  623.26
   167.4  623.48     177  623.75   186.7  623.79   196.4  623.79     206  623.84
   215.7  623.86
#Mann= 3 , 0 , 0
       0      .1       0    84.6    .045       0     105      .1       0
Bank Sta=84.6,105
XS Rating Curve= 0 ,0
Exp/Cntr=0.3,0.1

Chan Stop Cuts=-1
Use User Specified Reach Order=0
Composite Channel Slope=5